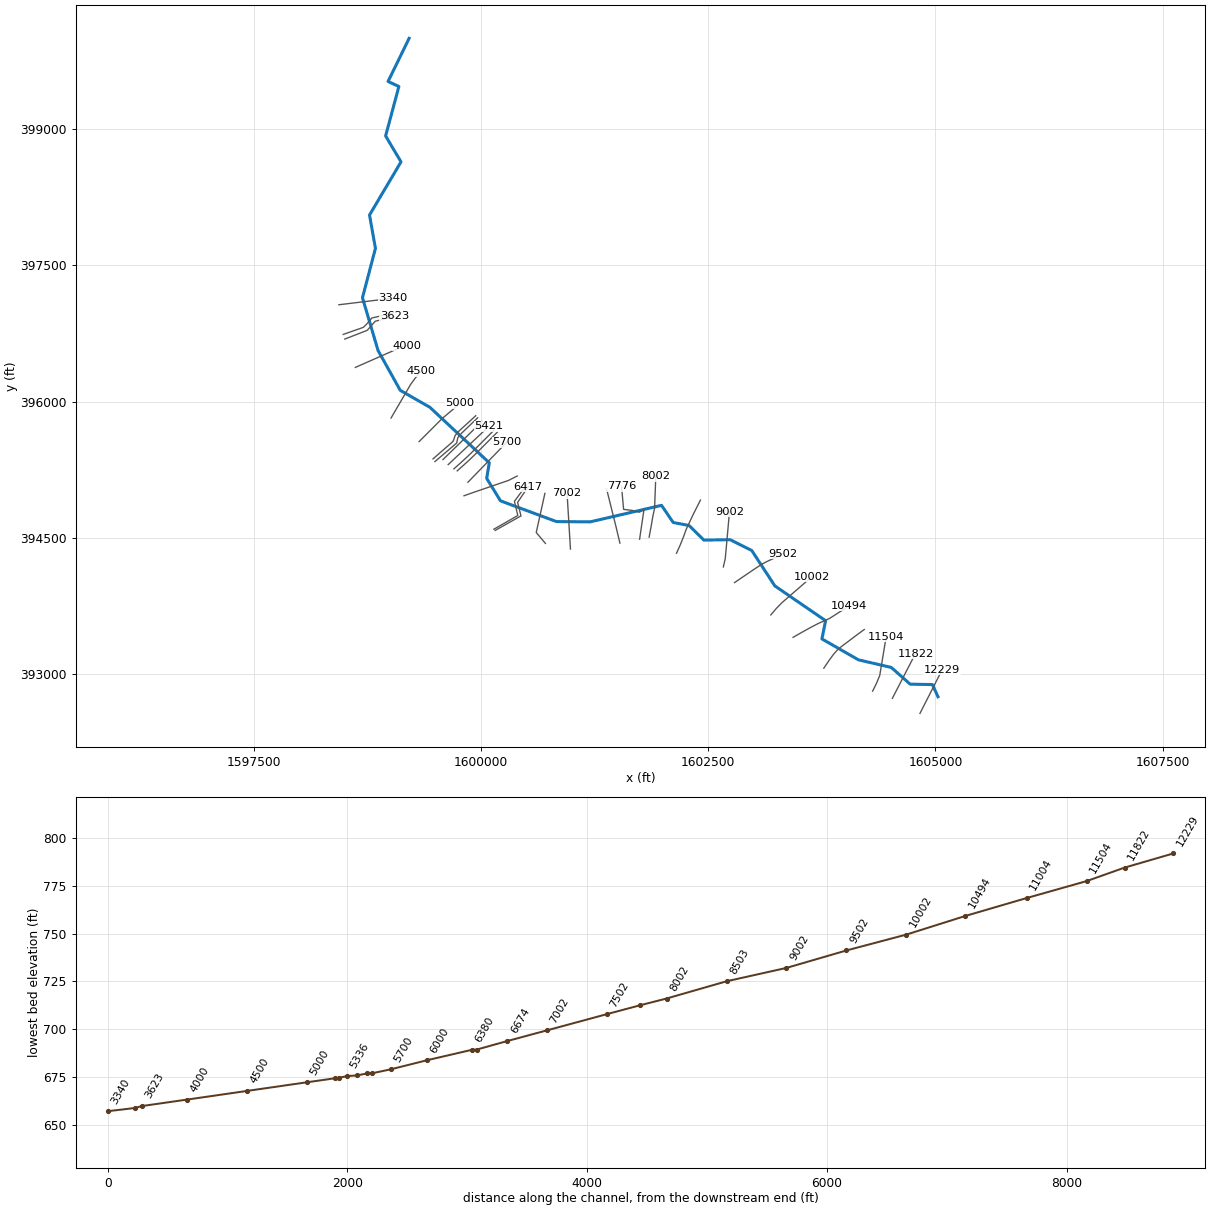
--- HUPPRN.prj (project) ---

Proj Title=HUPPRN
Current Plan=p01
Default Exp/Contr=0,0
English Units
Geom File=g01
Flow File=f01
Plan File=p01
BEGIN DESCRIPTION:
---------- MODELED AS PART OF WVEMD CTP PROGRAM, 2023----------
Stream Name: Hupp Run
Flood Zone:  AFH
Wetzel County, WV
HEC-RAS Version: RAS 6.3
Vertical Datum: NAVD88
Projection: NAD 1983 StatePlane West Virginia S FIPS 4702 (US Feet)
Terrain: 1-meter West Virginia FEMA R3 South Central (collected 2018-2020)
Land Use: 2019 NLCD
Hydrologic Method:
WV SIR2010-5033 regression equations
Additional Model Notes:
None
END DESCRIPTION:
DSS Export Rating Curves= 0
DSS Export Rating Curve Sorted= 0
DSS Export Volume Flow Curves= 0
DXF OffsetX= 0
DXF OffsetY= 0
DXF ScaleX= 0
DXF ScaleY= 0

--- HUPPRN.p01 (plan) ---

Plan Title=Floodplain
Program Version=6.30
Short Identifier=Floodplain
Geom File=g01
Flow File=f01
Subcritical Flow
K Sum by GR= 0
Std Step Tol= 0.01
Critical Tol= 0.01
Num of Std Step Trials= 20
Max Error Tol= 0.3
Flow Tol Ratio= 0.001
Split Flow NTrial= 30
Split Flow Tol= 0.02
Split Flow Ratio= 0.02
Log Output Level= 0
Friction Slope Method= 1
Unsteady Friction Slope Method= 2
Unsteady Bridges Friction Slope Method= 1
Parabolic Critical Depth
Global Vel Dist= 0 , 0 , 0
Global Log Level= 0
CheckData=True
Encroach Param=-1 ,0,0, 0
Mapping Interval=1HOUR
Computation Time Step Use Courant=        0
Computation Time Step Use Time Series=    0
Computation Time Step Count To Double=0
Computation Time Step Max Doubling=0
Computation Time Step Max Halving=0
Computation Time Step Residence Courant=0
Run HTab= 0
Run UNet= 0
Run Sediment= 0
Run PostProcess= 0
Run WQNet= 0
Run RASMapper= 0
UNET Theta= 0
UNET Theta Warmup= 0
UNET ZTol= 0
UNET ZSATol= 0
UNET MxIter= 0
UNET Max Iter WO Improvement= 0
UNET MaxInSteps= 0
UNET DtIC= 0
UNET DtMin= 0
UNET MaxCRTS= 0
UNET WFStab= 0
UNET SFStab= 0
UNET WFX= 1
UNET SFX= 1
UNET Gravity=32.17405
UNET 1D Methodology=Finite Difference
UNET DSS MLevel= 1
UNET Pardiso=0
UNET DZMax Abort= 0
UNET Use Existing IB Tables= 0
UNET Froude Reduction=False
UNET Froude Limit= 0
UNET Froude Power= 0
UNET D1 Cores= 0
UNET WindReference=Eulerian
UNET WindDragFormulation=Hsu (1988)
UNET D2 Coriolis=0
UNET D2 Cores= 0
UNET D2 Theta= 1
UNET D2 Theta Warmup= 1
UNET D2 Z Tol= 0.01
UNET D2 Volume Tol= 0.01
UNET D2 Max Iterations= 20
UNET D2 Equation= 0
UNET D2 RampUpFraction=0.1
UNET D2 TimeSlices= 1
UNET D2 Turbulence Formulation=Non-Conservative (original)
UNET D2 Eddy Viscosity=0.3
UNET D2 Transverse Eddy Viscosity=0.1
UNET D2 Smagorinsky Mixing=0
UNET D2 BCVolumeCheck=0
UNET D2 Cores=0
UNET D2 SolverType=PARDISO (Direct)
UNET D2 Minimum Iterations= 3
UNET D2 Maximum Iterations= 30
UNET D2 Restart Number= 10
UNET D2 Relaxation Coeff=1.3
UNET D2 SOR Precondition Iterations= 10
UNET D2 ILUT Maximum Fill= 8
UNET D2 ILUT Tolerance=1E-08
UNET D2 Convergence Tolerance=0.00001
UNET D1D2 MaxIter= 0
UNET D1D2 ZTol=0.01
UNET D1D2 QTol=0.1
UNET D1D2 MinQTol=1
Write IC File= 0
Write IC File at Fixed DateTime=0
Write IC File at Sim End=0
Echo Input=False
Echo Parameters=False
Echo Output=False
Write Detailed= 0
HDF Write Warmup=0
HDF Write Time Slices=0
HDF Flush=0
HDF Compression= 1
HDF Chunk Size= 1
HDF Spatial Parts= 1
HDF Use Max Rows=0
HDF Fixed Rows= 1
Calibration Method= 0
Calibration Iterations= 20
Calibration Max Change=0.05
Calibration Tolerance=0.2
Calibration Maximum=1.5
Calibration Minimum=0.5
Calibration Optimization Method= 1
WQ AD Non Conservative
WQ ULTIMATE=-1
WQ Max Comp Step=1HOUR
WQ Output Interval=15MIN
WQ Output Selected Increments= 0
WQ Output face flow=0
WQ Output face velocity=0
WQ Output face area=0
WQ Output face dispersion=0
WQ Output cell volume=0
WQ Output cell surface area=0
WQ Output cell continuity=0
WQ Output cumulative cell continuity=0
WQ Output face conc=0
WQ Output face dconc_dx=0
WQ Output face courant=0
WQ Output face peclet=0
WQ Output face adv mass=0
WQ Output face disp mass=0
WQ Output cell mass=0
WQ Output cell source sink temp=0
WQ Output nsm pathways=0
WQ Output nsm derived pathways=0
WQ Create Restart=0
WQ Fixed Restart=0
WQ System Summary=0
WQ Write To DSS=0
Sorting and Armoring Iterations= 10
XS Update Threshold= 0.02
Bed Roughness Predictor= 0
Hydraulics Update Threshold= 0.02
Energy Slope Method= 1
Volume Change Method= 1
Sediment Retention Method= 0
Sediment TS Multiplier= 1
Warm Up Method= 0
XS Weighting Method= 0
Number of US Weighted Cross Sections= 1
Number of DS Weighted Cross Sections= 1
Upstream XS Weight=0
Main XS Weight=1
Downstream XS Weight=0
Number of DS XS's Weighted with US Boundary= 1
Upstream Boundary Weight= 1
Weight of XSs Associated with US Boundary= 0
Number of US XS's Weighted with DS Boundary= 1
Downstream Boundary Weight= 0.5
Weight of XSs Associated with DS Boundary= 0.5
Percentile Method= 0
Sediment Output Level= 3
Mass or Volume Output= 0
Output Increment Type= 1
Profile and TS Output Increment= 1
Transport Output Increment 1
XS Output Flag= 0
XS Output Increment= 10
Read HDF5 Sediment Hotstart= 0
Sediment Hotstart Type= 0
Write Gradation File= 0
Read Gradation Hotstart= 0
Write HDF5 File= 1
Write Binary Output= 1
Write DSS Sediment File= 0
DSS Sediment Output Type= 1
SV Curve= 0
Specific Gage Flag= 0
Subcell Erosion Methods= 0
Subcell Deposition Methods= 0
Advection Scheme= 1
Matrix Solver= 0
Implicit Weighting Factor= 1
Maximum Outer Loop Convergence Iterations= 5
Convergence Maximum Absolute= 0.001
Convergence RMSE= 0.0001
Grain Fractions Max Abs Error= 0.001
Max Subgrid Regions= 1
Max Subgrid Length Scale= 3.402823E+38
Initial Layer Thickness= 3.402823E+38
Min Layer Thickness= 3.402823E+38
Max Layer Thickness= 3.402823E+38
Number of Layers= 5

--- HUPPRN.f01 (steady flow) ---

Flow Title=Flow
Program Version=4.00
Number of Profiles=1
Profile Names=F01pct
River Rch & RM=HUPPRN,Main,12229
     635
River Rch & RM=HUPPRN,Main,10494
     774
River Rch & RM=HUPPRN,Main,6417
    1320
River Rch & RM=HUPPRN,Main,2568
    1530
Boundary for River Rch & Prof#=HUPPRN,Main      ,1
Up Type=0
Dn Type=3
Dn Slope=0.011007

--- HUPPRN.g01 (geometry) ---

Geom Title=Geometry
Program Version=6.31

River Reach=HUPPRN          ,Main
Reach XY= 30
     1605027.242      392751.712     1604966.539      392885.491
     1604722.023      392889.848     1604513.296      393074.205
     1604152.938      393157.594     1603750.885      393388.189
     1603791.303      393588.577     1603233.109      393971.484
      1602979.54      394360.348     1602742.563        394479.9
     1602452.404      394475.645     1602289.456      394636.041
     1602114.595      394669.652     1601986.534      394858.127
     1601201.574      394676.459      1600830.58      394679.437
     1600214.902      394907.801     1600063.098      395154.716
     1600091.684      395326.192     1599438.521      395937.056
     1599111.962      396124.096     1598867.974      396562.504
     1598696.532      397143.274      1598839.29      397686.813
     1598774.079      398053.754     1599120.774      398638.886
     1598951.139      398923.631     1599097.092      399468.337
     1598978.126      399523.414     1599209.705      399998.295

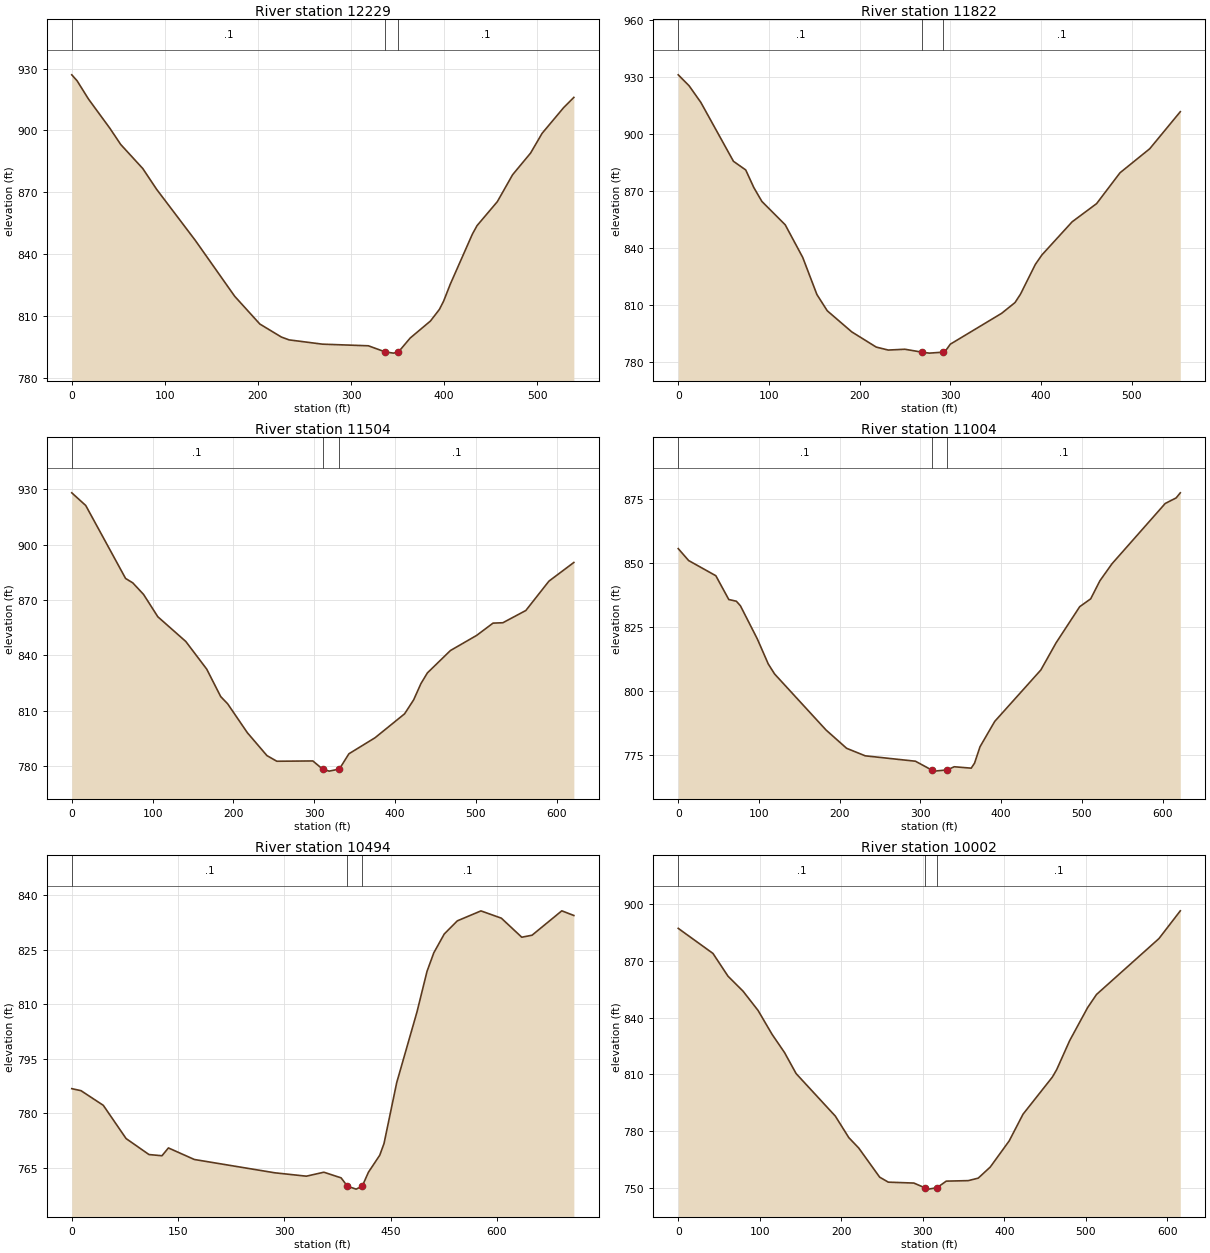
Type RM Length L Ch R = 1 ,12229   ,406.6,407.1,405.7
XS GIS Cut Line= 2
1604829.54993743392568.4999727491605073.90703774393049.258360798
#Sta/Elev= 30
       0  926.94     5.7  924.06      18  915.15      41  900.95    52.5  893.17
    76.3  881.43    91.2  871.33   132.8   846.5     175  819.44     202  805.97
   225.1  799.66   233.4  798.27   269.3  796.19   318.6   795.4   336.6  792.44
   345.5  791.84  350.93 792.425   363.5  799.16   385.3  807.44   394.9  813.07
   399.4  817.06   406.5  825.23   430.3   849.6   435.3  853.72   457.1  865.36
   473.5  878.43   492.8  888.94   505.2  898.54   528.5   911.1   539.3  915.99
#Mann= 3 ,-1,0
       0      .1       0   336.6    .045       0  350.93      .1       0
Bank Sta=336.6,350.93
XS Rating Curve= 0 ,0
Exp/Cntr(USF)=0,0
Exp/Cntr=0.3,0.1

Type RM Length L Ch R = 1 ,11822   ,315.6,317.6,321.6
XS GIS Cut Line= 2
1604526.09251519392734.4354920281604779.54197272393226.559326603
#Sta/Elev= 30
       0  931.32      12  925.53    24.9  916.79    60.9  885.67    74.4  881.12
    83.4  871.77    92.2  864.52     118  852.14   137.3  834.91   152.9  815.37
   164.3  806.79   191.3  795.66   218.3  787.62   231.6  786.05   249.8  786.48
   269.2  784.91   276.8  784.43   291.6784.9213   294.8  785.68     300  789.15
   356.5  805.41   371.3   811.1   377.3  815.48   393.8  831.29     401  836.26
   434.3  853.73   461.3  863.34   487.1  879.61   519.9  892.31   553.6  911.86
#Mann= 3 ,-1,0
       0      .1       0   269.2    .045       0   291.6      .1       0
Bank Sta=269.2,291.6
XS Rating Curve= 0 ,0
Exp/Cntr(USF)=0,0
Exp/Cntr=0.3,0.1

Type RM Length L Ch R = 1 ,11504   ,504.2,499.9,488.9
XS GIS Cut Line= 6
 1604308.4999125392812.809488758  1604352.367935  392902.0248615
1604386.91445383392985.7553370891604399.32551825393059.771921337
1604415.64832026393158.4387187511604457.36805309393411.134735674
#Sta/Elev= 30
       0  928.05    17.3  921.19    66.6  881.68    75.5   879.3    88.8  873.06
   106.5  860.94   141.1  847.56     167  832.57   184.3  817.71   192.8  813.86
   217.2   798.2   241.5  785.77   253.7  782.72   298.3  782.88   310.4  778.45
   318.5  777.37  331.06 778.484   342.9  786.76   375.3  795.46   411.8   808.4
     423  815.97     432  824.75     440  830.55   468.5  842.66     501  850.87
   521.2   857.5   533.4  857.71   561.8  864.34   590.4  880.24   621.2  890.34
#Mann= 3 ,-1,0
       0      .1       0   310.4    .045       0  331.06      .1       0
Bank Sta=310.4,331.06
XS Rating Curve= 0 ,0
Exp/Cntr(USF)=0,0
Exp/Cntr=0.3,0.1

Type RM Length L Ch R = 1 ,11004   ,508.6,510.8,502.1
XS GIS Cut Line= 6
1603772.03346576 393065.827355431603826.57928842393147.287822425
1603880.19696334393220.6744866671603931.22113951393277.910920754
1604140.70628484393436.0949875861604216.30980818 393491.54632026
#Sta/Elev= 30
       0  855.62    12.9  850.95    46.6  845.01    62.6   835.7      72  835.03
      77  833.26      98  820.25   111.5  810.48   119.4  806.54     183  784.65
   208.6  777.46   231.6  774.52   293.8  772.41   313.8  768.99   316.8  768.53
  333.05768.9992   341.9  770.24   362.9  769.69     367  771.63   373.8  778.07
     392  787.98   449.2  808.14     468  818.74   497.3   832.9   510.9  835.97
   522.3  843.04   537.3   849.7   603.2  873.29   616.7  875.46   621.9  877.46
#Mann= 3 ,-1,0
       0      .1       0   313.8    .045       0  333.05      .1       0
Bank Sta=313.8,333.05
XS Rating Curve= 0 ,0
Exp/Cntr(USF)=0,0
Exp/Cntr=0.3,0.1

Type RM Length L Ch R = 1 ,10494   ,487.7,491.9,494.6
XS GIS Cut Line= 6
1603433.49313234393405.423132926  1603527.082184393458.863314763
1603620.13252284393510.5702323321603709.57361692393557.421188504
1603834.84469184393613.3085439211604050.39708225393751.877164423
#Sta/Elev= 30
       0  786.82      13  786.27    44.5  782.24    76.7  773.09     109   768.7
   127.3  768.37   136.4  770.52     173  767.34   286.5  763.68   331.1  762.75
   355.8  763.84   380.1  762.29   389.1  759.98   401.4  759.19     410  760.02
   418.7  763.84   434.6  768.49   440.7  771.74   458.6  788.48   487.2  807.91
   501.4  819.09   510.9  824.16   525.7  829.36   544.2  832.98   577.5  835.71
   606.3  833.71   635.1  828.47   649.6  829.02   691.6  835.73   708.6  834.45
#Mann= 3 ,-1,0
       0      .1       0   389.1    .045       0     410      .1       0
Bank Sta=389.1,410
XS Rating Curve= 0 ,0
Exp/Cntr(USF)=0,0
Exp/Cntr=0.3,0.1

Type RM Length L Ch R = 1 ,10002   ,499.7,499.7,495.8
XS GIS Cut Line= 6
1603188.45031534393652.1591880021603251.25530784393725.731547415
1603312.94416083393788.4200703351603369.59365384393837.571546838
1603445.12532692393903.1075050091603638.67579284394071.042864665
#Sta/Elev= 30
       0  887.04    42.6  873.82    61.1  861.78    79.5  853.91      98  843.69
   115.1  831.14   130.4  821.52   144.6  810.43   192.7     788   209.3  776.61
   221.5  771.11   247.1  755.78   257.7  753.15   289.1  752.67   302.1750.2455
   306.9  749.47   317.4  750.22   328.8  753.69   355.8  753.95     368  755.27
   382.7  761.09     406  774.92   422.9  788.96     459  808.61   464.3  812.55
   480.1  827.75   502.2  845.24   513.1  852.16   589.7  881.65   615.9  896.29
#Mann= 3 ,-1,0
       0      .1       0   302.1    .045       0   317.4      .1       0
Bank Sta=302.1,317.4
XS Rating Curve= 0 ,0
Exp/Cntr(USF)=0,0
Exp/Cntr=0.3,0.1

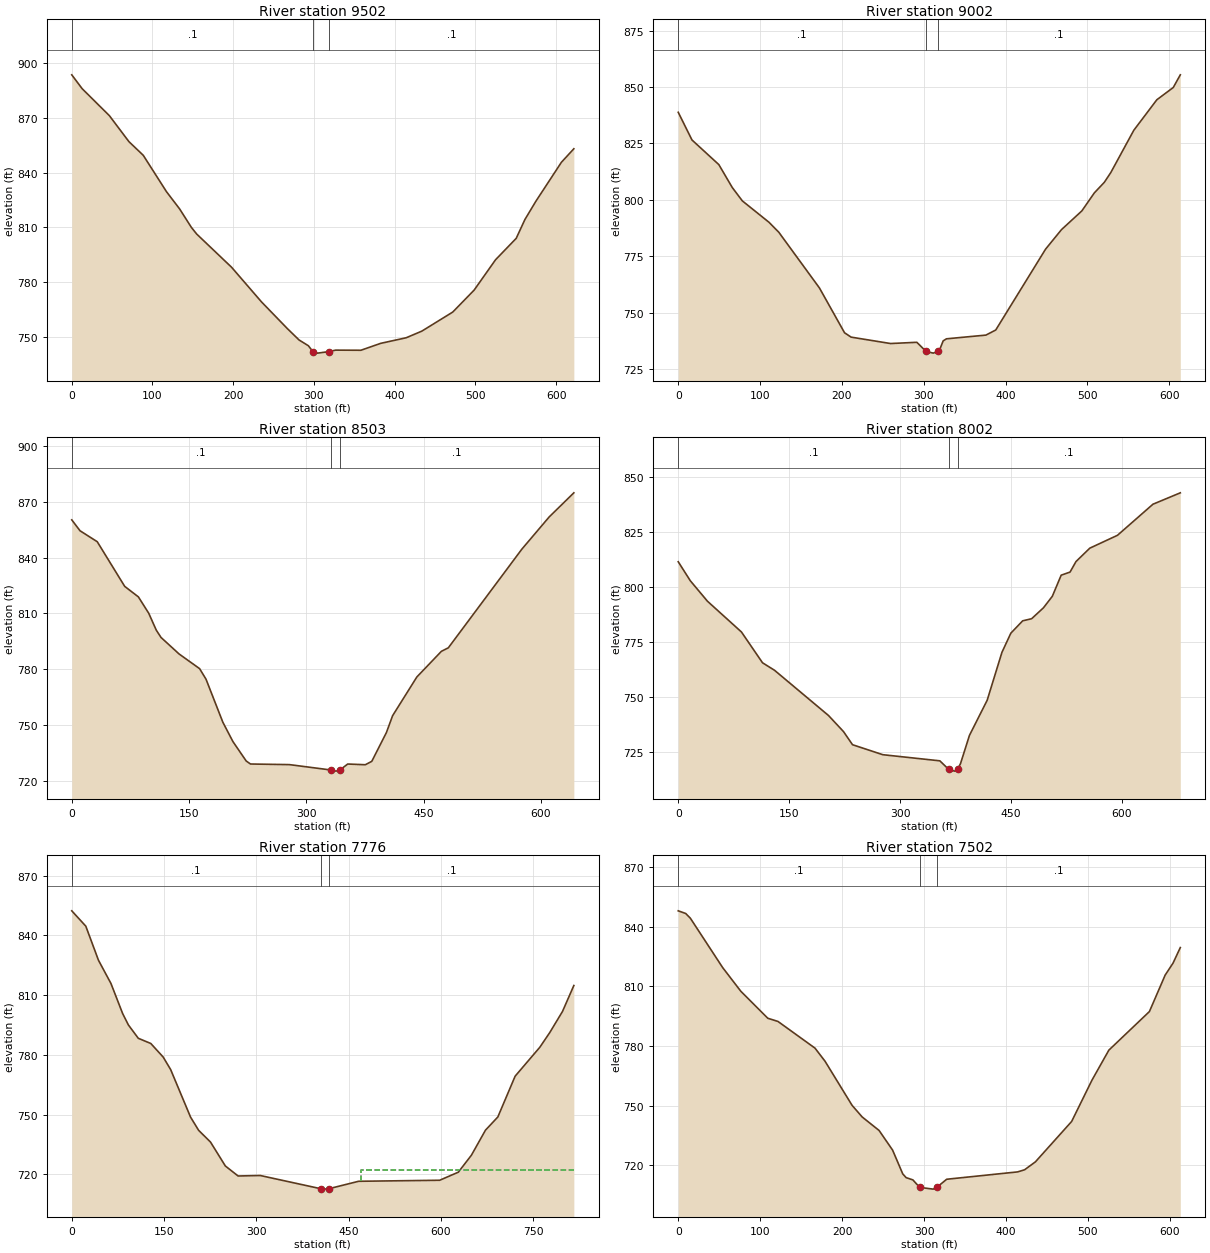
Type RM Length L Ch R = 1 ,9502    ,495.5,500.3,509.4
XS GIS Cut Line= 6
1602789.54166435 394008.031507761603001.51564984394152.014487505
1603084.62703218394207.6292056741603151.70038883 394242.59206225
1603233.90429267394280.6950044181603321.42281842 394328.04661575
#Sta/Elev= 30
       0   893.5    12.8  885.95    46.6  871.15    70.8  856.94    88.6  849.44
   117.4   829.5   133.7  820.06   148.2  809.99   154.8  806.34     198  788.17
   235.2  769.15   267.2  754.56   281.6  748.38   293.1  745.23   298.9  741.94
   304.6  741.18   319.1  742.04   326.8  742.82   358.2  742.75   382.7  746.53
   414.3  749.59   433.7  753.22     472  763.66   498.5  775.69     525  792.28
   550.6     804   561.4  814.32     575  824.33   606.6  845.64     622  853.03
#Mann= 3 ,-1,0
       0      .1       0   298.9    .045       0   319.1      .1       0
Bank Sta=298.9,319.1
XS Rating Curve= 0 ,0
Exp/Cntr(USF)=0,0
Exp/Cntr=0.3,0.1

Type RM Length L Ch R = 1 ,9002    ,500,498.9,495
XS GIS Cut Line= 6
1602666.56750084394180.1433682591602687.38438834394272.425007835
1602695.59500185394359.5396630021602717.94207001394608.538836926
1602725.76390475394695.6885970091602734.14413734394789.063410252
#Sta/Elev= 30
       0  838.79    16.8  826.52    49.6  815.61      66  805.46    78.3  799.54
   110.8  790.08   122.8  785.67   172.5  760.96   203.2  741.09   211.2  739.16
   259.4  736.32   291.5  736.87  302.86732.8105   311.6  732.07  317.23 732.832
   319.6  733.79   323.7  737.51   327.7  738.41   375.9  740.06   387.9  742.31
   448.8  778.15   468.2  786.78   493.1  795.09   508.4  803.09   520.5  807.73
   528.5   812.1   556.6  830.83   584.7  844.33   604.8  849.78   613.4  855.39
#Mann= 3 ,-1,0
       0      .1       0  302.86    .045       0  317.23      .1       0
Bank Sta=302.86,317.23
XS Rating Curve= 0 ,0
Exp/Cntr(USF)=0,0
Exp/Cntr=0.3,0.1

Type RM Length L Ch R = 1 ,8503    ,496.3,501.1,500.9
XS GIS Cut Line= 6
1602150.99832201394330.836964503 1602192.8351806394423.577592671
1602229.07657792394514.2942747621602258.05585067394594.993260339
1602332.81816834394753.9525880961602414.36393701394915.841700003
#Sta/Elev= 30
       0  860.28    10.6  854.41    32.6  848.52    67.7   824.5    85.2  818.84
    98.4  810.06   108.1  800.94   114.2     797   137.2  788.15   163.5  780.23
   171.7  774.55   193.2  751.43   206.1     741   223.1  730.54   228.6  728.93
   278.3   728.6   330.9  725.74   338.1   725.1  343.07725.7598   352.9  728.92
   375.4  728.54   383.7  730.37   402.4  745.86   410.3  754.91   441.3  775.74
   472.7  789.55   481.6  791.45   575.6  844.52   610.6  861.87   642.1  874.83
#Mann= 3 ,-1,0
       0      .1       0   330.9    .045       0  343.07      .1       0
Bank Sta=330.9,343.07
XS Rating Curve= 0 ,0
Exp/Cntr(USF)=0,0
Exp/Cntr=0.3,0.1

Type RM Length L Ch R = 1 ,8002    ,220.3,225.2,237.3
XS GIS Cut Line= 6
1601849.94511834394508.528210178  1601872.097305394626.288473338
1601891.51688559394741.239030838  1601910.183843394825.511828169
1601913.88626343394925.4433868381601923.37213685395181.517677844
#Sta/Elev= 30
       0  811.45    16.3  802.81    39.5  793.48    85.5  779.46     114  765.43
   130.2  762.03   203.2  741.43   223.5   734.1   235.7  728.12   276.7  723.57
   353.8  720.78   365.8  716.88   373.8  716.09   377.8  716.85   381.8  719.56
   393.8  732.34   417.8  748.36   437.8  770.21   449.8  778.91   465.8  784.54
   477.9   785.5   493.9  790.47   505.9  795.71   517.9  805.33   529.9  806.75
   537.9  811.53   556.6  817.64     594  823.49     642  837.65     679  842.84
#Mann= 3 ,-1,0
       0      .1       0   365.8    .045       0   377.8      .1       0
Bank Sta=365.8,377.8
XS Rating Curve= 0 ,0
Exp/Cntr(USF)=0,0
Exp/Cntr=0.3,0.1

Type RM Length L Ch R = 1 ,7776    ,275.3,274.8,262.3
XS GIS Cut Line= 6
1601745.28000677394485.549361138 1601792.9124252394809.656903921
 1601742.1735447394782.7342326351601663.47650556394802.408492421
1601569.24715606394813.7988533491601546.46643421395067.493255847
#Sta/Elev= 30
       0  852.38    22.8  844.67    43.4  827.53    63.7  815.84    82.7  800.72
      92  795.02   108.1  788.31   128.4   785.7   148.6  778.85   160.7  772.57
     193   748.7   206.1  742.06   225.4  736.16   249.6  724.11   270.3  719.09
   306.2  719.34  404.36  712.71   414.6  712.49  418.22  712.73   466.1  716.43
   597.8  716.95   628.1  721.01   649.4  729.56   672.2  742.12   692.3  748.76
   720.4  769.26   760.6  783.83   776.7   791.2   797.4  801.82   815.8  814.84
#Mann= 3 ,-1,0
       0      .1       0  404.36    .045       0  418.22      .1       0
#XS Ineff= 2 , 0
                          470.26          722.18
Permanent Ineff=
       F       F
Bank Sta=404.36,418.22
XS Rating Curve= 0 ,0
Exp/Cntr(USF)=0,0
Exp/Cntr=0.3,0.1

Type RM Length L Ch R = 1 ,7502    ,501.7,500,497.7
XS GIS Cut Line= 6
1601528.73808359394442.1923848391601506.87592259394533.480588093
1601486.70207842   394618.6808771601468.72015901394691.493723512
1601405.05394776394946.1559438411601382.31646043395037.106877416
#Sta/Elev= 30
       0  848.06     9.1  846.72    14.8  844.34    54.2  819.49    76.4  807.54
   109.3  793.96   121.7  792.35   166.9  778.91   179.2  772.28   212.2  750.07
   224.5  744.23   245.1  737.45   261.6  727.55     274  715.56   278.1   713.7
   286.4  712.53   294.6  708.79   311.1   707.9  315.48 708.778   327.6  712.87
   414.2  716.58   422.7  717.65   435.9  721.65   480.1  741.98   504.9  762.78
   525.5  777.89     575  797.33   594.2  815.68   603.8  821.71   612.7  829.56
#Mann= 3 ,-1,0
       0      .1       0   294.6    .045       0  315.48      .1       0
Bank Sta=294.6,315.48
XS Rating Curve= 0 ,0
Exp/Cntr(USF)=0,0
Exp/Cntr=0.3,0.1

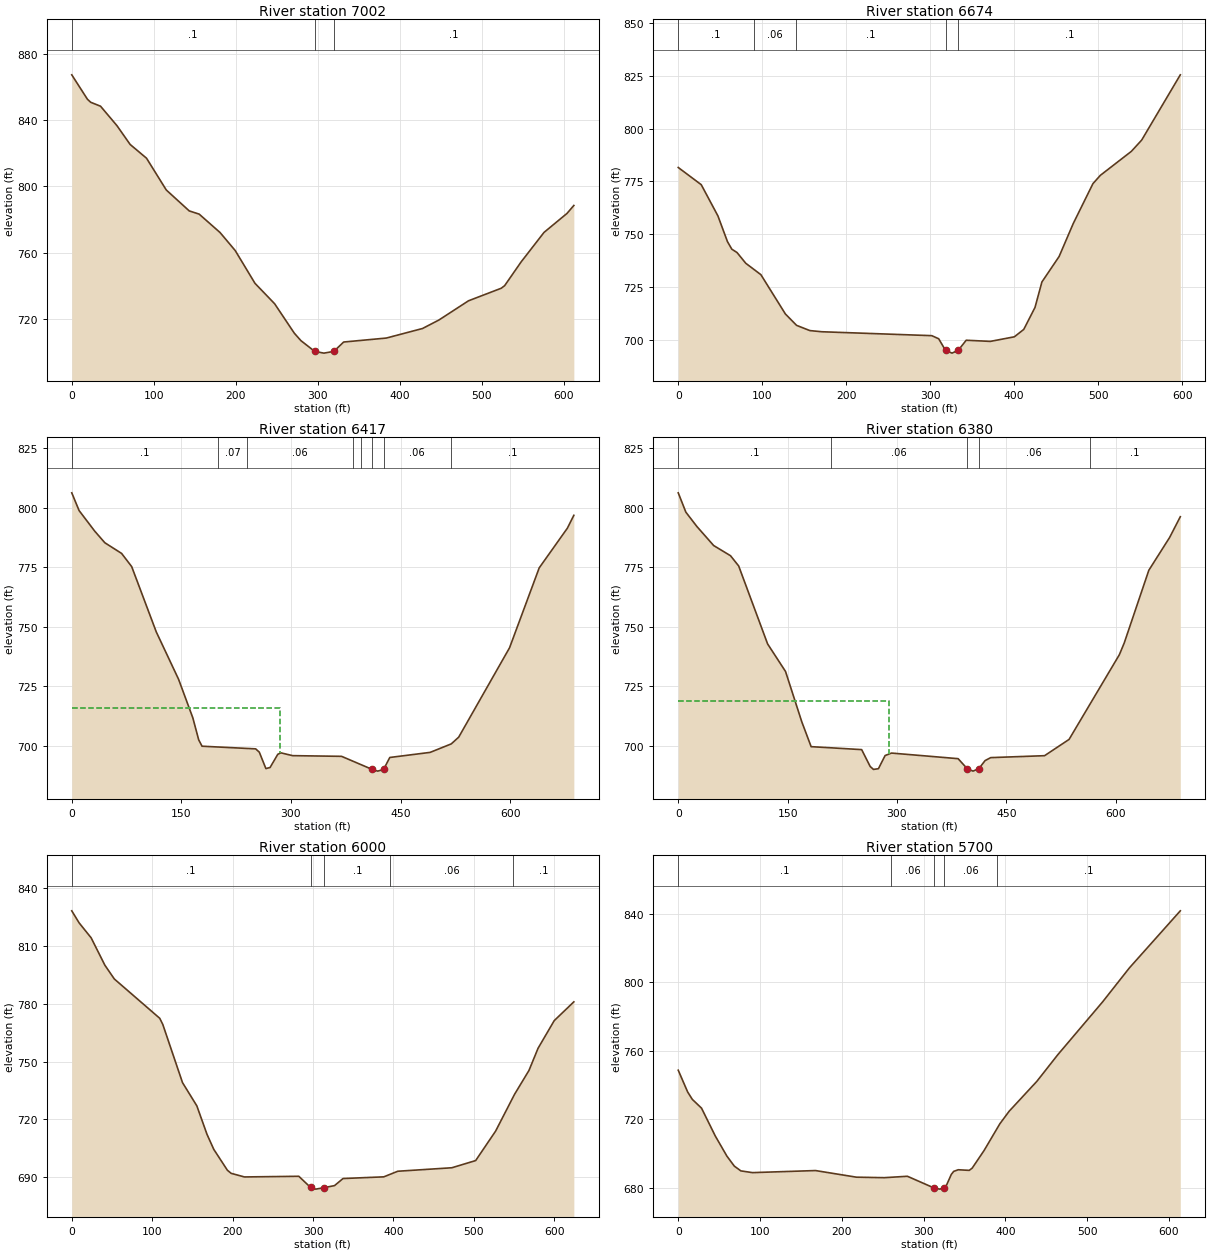
Type RM Length L Ch R = 1 ,7002    ,330.1,327.8,324.4
XS GIS Cut Line= 6
1600984.57512993394377.4618712511600978.87829092394471.038455755
1600973.56235668394558.3768637631600969.00495109394633.238262594
1600962.92950392394733.053679749 1600947.3593251394988.830071092
#Sta/Elev= 30
       0  867.36    19.1  852.63    23.1  850.79    35.1  848.42    55.2  836.64
    71.2  825.35    91.2  817.04   115.3  797.87   143.3  785.24   155.4  783.31
   180.9   772.2   199.4  761.32   223.5  741.55   247.5  729.21   271.5  711.45
   279.6  706.93  296.38700.4652   307.6  699.42   319.7  700.47   331.7  706.12
   383.8  708.52   427.9  714.28   447.9   719.4     484     731     524  738.59
   528.1  740.14   548.1  754.41   576.1  772.26   604.2  783.75   612.5  788.52
#Mann= 3 ,-1,0
       0      .1       0  296.38    .045       0   319.7      .1       0
Bank Sta=296.38,319.7
XS Rating Curve= 0 ,0
Exp/Cntr(USF)=0,0
Exp/Cntr=0.3,0.1

Type RM Length L Ch R = 1 ,6674    ,253.3,256.5,259.7
BEGIN DESCRIPTION:
Structure XS 4
END DESCRIPTION:
XS GIS Cut Line= 3
1600709.32450766394439.1276831421600608.05837912 394558.80583506
1600703.18716654394989.442603929
#Sta/Elev= 30
       0  781.61    27.4  773.48    47.3   758.7    58.6  746.59    63.8  743.02
      70  741.43    80.4  736.36    98.4  730.98   127.6   712.4   140.9  707.03
   156.7  704.56   170.8  704.01   301.9  702.16   310.1   700.7   318.3  695.19
     326  693.91  333.41 695.254   342.9     700   371.6  699.45   400.2  701.62
   411.4  705.11   424.8   715.5     433  727.51   453.5  739.56   470.3  755.11
   493.8  773.99   502.6   777.9   539.5  789.22   551.8  794.55   597.8  825.38
#Mann= 5 ,-1,0
       0      .1       0      90     .06       0     140      .1       0
   318.3    .045       0  333.41      .1       0
Bank Sta=318.3,333.41
XS Rating Curve= 0 ,0
Exp/Cntr(USF)=0,0
Exp/Cntr=0.3,0.1

Type RM Length L Ch R = 1 ,6417    ,37.6,37.6,37.6
BEGIN DESCRIPTION:
Structure XS 3
END DESCRIPTION:
XS GIS Cut Line= 4
1600156.65693944394582.4345983881600440.20209937394741.698600556
1600403.37805263 394890.835989871600519.37379987395063.909009567
#Sta/Elev= 30
       0  806.27      10  798.84    31.5  790.15    45.3   785.3    68.2  780.83
      82   775.3   115.7  747.85   146.2  727.98   165.7   711.8   173.7  702.59
   178.3  699.88   251.7  698.77   256.7  697.38   265.7  690.49   271.4  690.94
     282  696.49   286.2   697.1   302.2  695.92   369.3  695.63  411.26690.1295
   418.8  689.42   426.8  690.15   435.3  695.15   490.5  697.29   519.4  700.85
   529.6  703.68   599.2  741.21   639.8  774.76   678.3   791.4   687.2  796.83
#Mann= 8 ,-1,0
       0      .1       0     200     .07       0     240     .06       0
  385.21      .1       0  395.21     .06       0  411.26    .045       0
   426.8     .06       0  518.83      .1       0
#XS Ineff= 2 , 0
          285.33  715.72
Permanent Ineff=
       F       F
Bank Sta=411.26,426.8
XS Rating Curve= 0 ,0
Exp/Cntr(USF)=0,0
Exp/Cntr=0.3,0.1

Type RM Length L Ch R = 1 ,6380    ,389.8,379.6,366.8
BEGIN DESCRIPTION:
Structure XS 2
END DESCRIPTION:
XS GIS Cut Line= 4
1600141.92732075394595.3230147481600405.21925497394746.301606399
1600368.39520822394902.8038050621600501.88237767395083.241634108
#Sta/Elev= 30
       0  806.18    10.5  798.05    25.6  792.04    48.6  784.05    71.7  779.78
    82.9  775.48   122.6  742.74   147.2  731.17   169.5  710.02   182.3  699.61
     210  699.12   251.6  698.37   263.3  691.29   267.8  690.06   274.6  690.36
   283.8  695.89   292.6  696.92   383.9  694.57   396.4  690.36   404.4  689.34
   412.5  690.42   420.9  693.76   428.6  695.01   502.5  695.82   536.1  702.65
   605.1  738.22   611.8  743.16   645.5  773.66   674.1  787.47   688.7  796.15
#Mann= 5 ,-1,0
       0      .1       0     210     .06       0   396.4    .045       0
   412.5     .06       0  564.28      .1       0
#XS Ineff= 2 , 0
          288.86  718.62
Permanent Ineff=
       F       F
Bank Sta=396.4,412.5
XS Rating Curve= 0 ,0
Exp/Cntr(USF)=0,0
Exp/Cntr=0.3,0.1

Type RM Length L Ch R = 1 ,6000    ,298,299.7,302.3
BEGIN DESCRIPTION:
Structure XS 1
END DESCRIPTION:
XS GIS Cut Line= 6
1599813.43508376394963.5269720851599901.71016967394995.122381344
1599984.49018784395023.4717340921600150.05120842395080.169455335
1600303.78613718395132.8166597491600397.80957118395180.707968175
#Sta/Elev= 30
       0  828.39     9.1  822.16    24.1  814.36    41.1  800.19    52.9     793
   109.4  772.56   113.2  769.36   137.7  739.15   155.5  727.09   168.2  712.24
   176.6  704.47   193.5  693.64   198.2  692.02   214.7  690.15   282.3  690.49
  296.99684.6861   303.5  683.82     314  684.62   326.7  685.64   337.3  689.32
     388   690.2   405.4  693.11   472.6  694.92   502.2  698.65     527  713.94
   550.5  733.02   568.5  745.47   579.8  756.98   599.9  771.35   624.3   781.1
#Mann= 5 ,-1,0
       0      .1       0  296.99    .045       0     314      .1       0
  396.26     .06       0  548.76      .1       0
Bank Sta=296.99,314
XS Rating Curve= 0 ,0
Exp/Cntr(USF)=0,0
Exp/Cntr=0.3,0.1

Type RM Length L Ch R = 1 ,5700    ,158.8,158.7,158.1
BEGIN DESCRIPTION:
Structure XS 4
END DESCRIPTION:
XS GIS Cut Line= 2
1599856.32994887395111.9948728591600283.89804718395552.860543601
#Sta/Elev= 30
       0   748.6    11.5   735.9    17.2  731.56    28.5  726.42    45.3  710.17
    59.6  698.34    68.6  692.56    76.6  689.77    90.8  688.75   167.9  689.96
     218  686.09     252   685.8   280.3  686.62   312.8  679.81   319.9  679.11
   325.5  679.88   328.4   681.7     334  687.71   336.9  689.47   342.5  690.43
   355.9  690.07   359.5  691.35   374.1  701.69   393.4   717.3   404.7  724.59
   438.7  742.12   464.1  757.56     519  788.48   551.8  808.36   614.1  841.72
#Mann= 5 ,-1,0
       0      .1       0     260     .06       0   312.8    .045       0
   325.5     .06       0     390      .1       0
Bank Sta=312.8,325.5
XS Rating Curve= 0 ,0
Exp/Cntr(USF)=0,0
Exp/Cntr=0.3,0.1

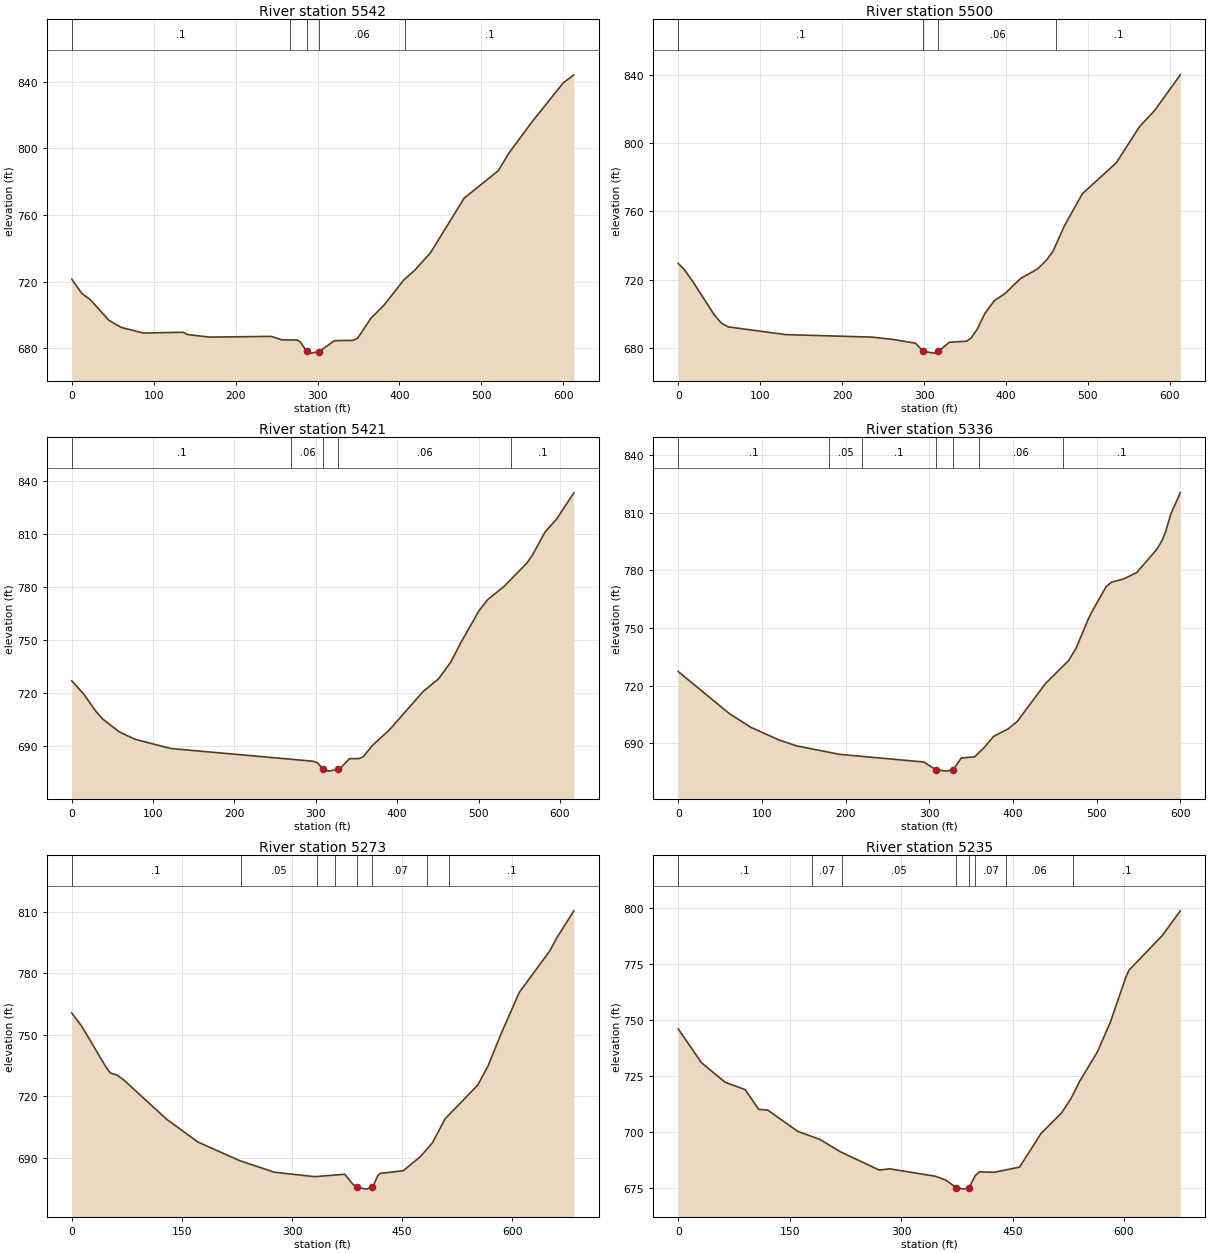
Type RM Length L Ch R = 1 ,5542    ,41.4,41.6,41.7
BEGIN DESCRIPTION:
Structure XS 3
END DESCRIPTION:
XS GIS Cut Line= 6
1599738.90482351395237.8826815591599809.03657301395300.333015974
1599873.83368751395359.2797484651599927.96153201395411.217964808
1599998.67267668395481.9284533071600179.86949275 395663.12330089
#Sta/Elev= 30
       0  721.46    12.3   712.9    22.6  709.15    45.2   696.8    60.5  692.45
    87.3   689.1   135.8  689.55   141.5  688.17   168.4  686.64   243.4  687.09
   256.5  684.99   275.4  684.92   279.4  683.46   286.7  678.01   292.3  677.02
     302  677.99   320.6  684.51   343.2   684.7   348.9  685.99     365   697.9
   381.2  705.92   405.5  721.12   418.8  726.91   437.8   737.3     479   770.2
   520.6  786.63   533.9   797.5     563  816.79   599.8  839.39   612.8  844.26
#Mann= 5 ,-1,0
       0      .1       0  266.52     .06       0   286.7    .045       0
     302     .06       0  406.52      .1       0
Bank Sta=286.7,302
XS Rating Curve= 0 ,0
Exp/Cntr(USF)=0,0
Exp/Cntr=0.3,0.1

Type RM Length L Ch R = 1 ,5500    ,79.1,78.9,78.6
BEGIN DESCRIPTION:
Structure XS 2
END DESCRIPTION:
XS GIS Cut Line= 6
1599702.38609326395259.8282167611599772.51784275395322.278551176
1599837.31495726395381.2252836671599891.44280176395433.163500011
1599962.15394643395503.873988509 1600143.3507625395685.068836093
#Sta/Elev= 30
       0  729.44     7.1  726.14    18.4  718.47    44.2  699.21    52.7  694.53
    61.2  692.31   131.2   687.8   236.7  686.33   262.2  684.95   289.6  682.79
     299  677.98   312.2  676.95   317.5 677.952     331  683.32   351.8  683.93
   357.5  685.75     365  691.02   374.4  700.31   385.7  707.61   398.9  711.88
   417.8  720.65   438.5  726.24   449.8  731.64   457.4  736.65   471.5  751.65
   493.2  770.28   534.7  788.48   562.9  809.54   581.8   819.3   612.8  839.98
#Mann= 4 ,-1,0
       0      .1       0     299    .045       0   317.5     .06       0
  461.52      .1       0
Bank Sta=299,317.5
XS Rating Curve= 0 ,0
Exp/Cntr(USF)=0,0
Exp/Cntr=0.3,0.1

Type RM Length L Ch R = 1 ,5421    ,85.5,85.5,85.7
BEGIN DESCRIPTION:
Structure XS 1
END DESCRIPTION:
XS GIS Cut Line= 2
1599639.48745805395306.5854105371600089.13668684395729.389909241
#Sta/Elev= 30
       0  727.08    14.5  719.69    30.1  709.56    37.9  705.51    58.4   698.2
    77.7  693.99   121.7  688.76   296.1  681.58   301.8  680.75   309.4 676.933
   315.9  675.95   327.2  676.97   330.1  677.57   341.3  682.98   353.2  683.06
   358.4   684.1   368.7  690.09   390.7  699.44   431.9     721   451.1  728.32
   465.9  737.67   478.5  748.87   500.5  766.66   511.2  773.02     531  780.37
   559.3  793.66   566.4  798.34   581.9   811.4   596.1  818.71   617.2  833.52
#Mann= 5 ,-1,0
       0      .1       0     270     .06       0   309.4    .045       0
   327.2     .06       0     540      .1       0
Bank Sta=309.4,327.2
XS Rating Curve= 0 ,0
Exp/Cntr(USF)=0,0
Exp/Cntr=0.3,0.1

Type RM Length L Ch R = 1 ,5336    ,60.9,62.7,64.4
BEGIN DESCRIPTION:
Structure XS 4
END DESCRIPTION:
XS GIS Cut Line= 2
1599582.06956317395361.7662445831600011.58524439395780.842308555
#Sta/Elev= 30
       0  727.34    61.2  705.47    86.7  698.37   120.2  691.83   141.4  688.73
   192.9  684.31   293.5  680.34   307.5  676.38   320.2  675.59   328.7   676.3
   338.2  682.38   354.2  683.02   365.5  687.75   376.8   693.6   394.1  697.48
   405.1  701.35     439  721.15   466.7   733.1   475.8  739.72   489.9  754.41
   494.6  758.56   511.4  771.46   518.2  773.88   532.4  775.45   548.1  778.83
     572  790.89   578.5  795.65   582.5     800   588.9  809.38   600.1  820.24
#Mann= 7 ,-1,0
       0      .1       0     180     .05       0     220      .1       0
   307.5    .045       0   328.7     .07       0     360     .06       0
     460      .1       0
Bank Sta=307.5,328.7
XS Rating Curve= 0 ,0
Exp/Cntr(USF)=0,0
Exp/Cntr=0.3,0.1

Type RM Length L Ch R = 1 ,5273    ,37.7,37.5,37.1
BEGIN DESCRIPTION:
Structure XS 3
END DESCRIPTION:
XS GIS Cut Line= 6
1599494.07850347395340.1413231321599732.69832638395543.713859546
1599745.37500447395601.8774413781599767.74561286395632.450606187
1599783.40503874395648.8557190121599963.86127981395821.855090616
#Sta/Elev= 30
       0  760.64    13.2  754.43    47.1  734.02    52.8  731.36    61.3  730.46
      71  727.97   128.9  708.94     172  697.69   228.6  688.66   276.1     683
   330.9  680.84   371.8  682.02   382.8  677.11   388.5  675.68   401.3  674.76
   408.5  675.75   411.4  677.04   416.7  681.35   419.9  682.43   451.4  683.74
   473.8  690.31   491.1  697.31   508.4  709.07   552.9  725.53     567  734.96
     584  750.01   609.4  770.74   650.9  790.93   660.4  797.27   683.7  810.51
#Mann= 8 ,-1,0
       0      .1       0     230     .05       0  333.66      .1       0
  357.88     .07       0   388.5    .045       0   408.5     .07       0
  483.76     .06       0  513.76      .1       0
Bank Sta=388.5,408.5
XS Rating Curve= 0 ,0
Exp/Cntr(USF)=0,0
Exp/Cntr=0.3,0.1

Type RM Length L Ch R = 1 ,5235    ,235.8,235.4,233.5
BEGIN DESCRIPTION:
Structure XS 2
END DESCRIPTION:
XS GIS Cut Line= 6
1599472.45358202395369.2231140491599692.43123126395561.610346263
1599705.10790935395592.9291980191599714.80183966395624.993736722
1599746.86637836395665.2608318361599942.23635836395844.225699013
#Sta/Elev= 30
       0  745.88    31.4  730.79    63.3  722.07    90.1  718.83   108.3  710.04
   120.5   709.7   160.9  700.21   190.9   696.6   217.7  691.22   270.6  682.94
   284.5  683.52   346.5  680.18   360.1  678.49   374.5  675.14   384.5  674.46
  391.73675.1663   399.8  680.51   405.7  682.17   425.5  681.96   459.5   684.3
   488.6  699.35   515.8  708.33   528.4  714.63   540.2   722.4   564.2  735.61
   581.7  748.89   602.5  768.84   606.7  772.04   651.4  787.44   675.9  798.53
#Mann= 8 ,-1,0
       0      .1       0     180     .07       0     220     .05       0
   374.5    .045       0  391.73     .05       0  399.52     .07       0
     441     .06       0     531      .1       0
Bank Sta=374.5,391.73
XS Rating Curve= 0 ,0
Exp/Cntr(USF)=0,0
Exp/Cntr=0.3,0.1

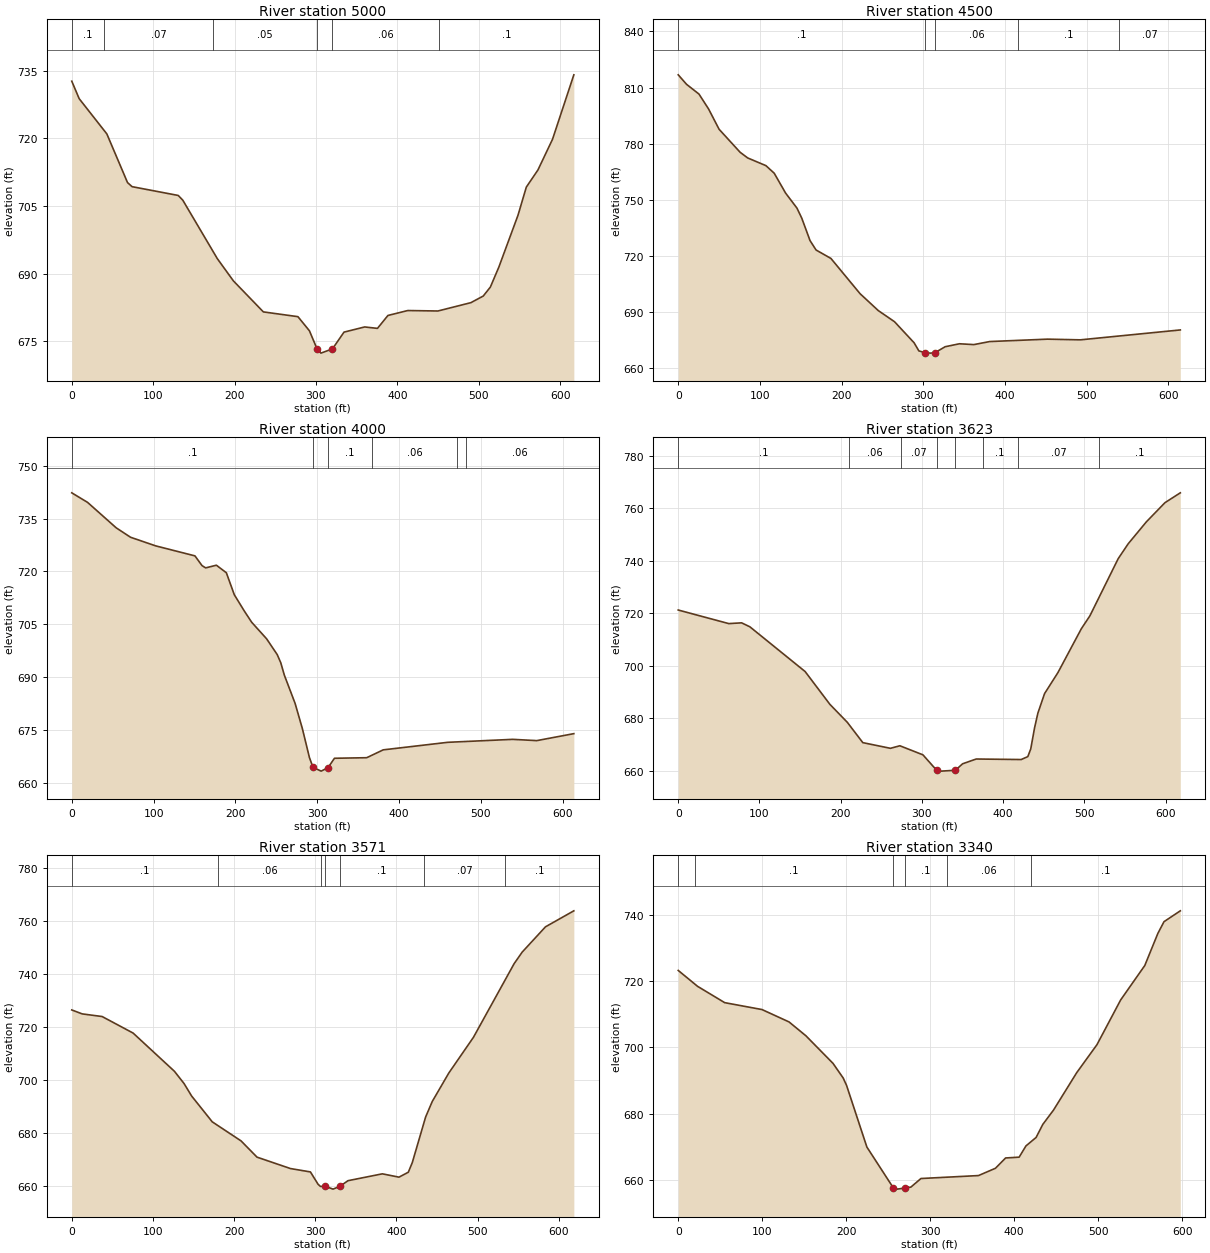
Type RM Length L Ch R = 1 ,5000    ,498.8,500,502.5
BEGIN DESCRIPTION:
Structure XS 1
END DESCRIPTION:
XS GIS Cut Line= 6
1599319.61979842395560.1117369231599500.81759876395741.306584507
1599571.52841534395812.0167449271599629.00894342 395860.66330117
 1599696.8949625 395918.216007591599769.19895175395981.833334416
#Sta/Elev= 30
       0  732.69     9.1  728.81    43.1  720.99    68.5  710.19    74.1  709.28
   130.8  707.33   136.4  706.29   178.8  693.32   198.6  688.37   235.4  681.49
   277.9  680.43     292   677.3  301.33673.3018   306.1  672.34   320.3  673.28
   334.5     677   359.9  678.15   375.6  677.83   388.5   680.7   412.8  681.79
   449.9  681.69   490.4  683.54   505.6  685.01   514.3  686.99   524.8  691.45
   548.3  702.95   558.5  709.18   572.8  712.99   590.7   719.8   616.9   734.1
#Mann= 6 ,-1,0
       0      .1       0      40     .07       0  173.75     .05       0
  301.33    .045       0   320.3     .06       0  451.55      .1       0
Bank Sta=301.33,320.3
XS Rating Curve= 0 ,0
Exp/Cntr(USF)=0,0
Exp/Cntr=0.3,0.1

Type RM Length L Ch R = 1 ,4500    ,503.1,500,495
XS GIS Cut Line= 6
1599010.96063884395819.0059041681599058.12327418395900.029364169
1599190.18009667 396126.896364511599227.90902384396191.713492095
1599280.00964142396262.6296888441599341.95407134396335.047851086
#Sta/Elev= 30
       0  816.79    10.2   811.7    25.4  806.49    37.1  798.55      50  787.66
    75.8  775.31    85.1  772.28   107.3  768.19   117.5  764.11   131.4   753.5
   145.3  745.46   151.2  740.07   161.3  728.08   168.7  723.03   186.9  718.51
   222.5  699.67   244.8  690.62   264.7  684.65   288.7  673.36   294.5  669.02
   302.6     668   309.1  667.83  314.05668.0165   326.7  671.26   344.2  672.84
   361.8  672.39   381.3  674.03   452.1  675.31   492.1  674.94   614.5  680.24
#Mann= 5 ,-1,0
       0      .1       0   302.6    .045       0  314.05     .06       0
  416.25      .1       0  539.25     .07       0
Bank Sta=302.6,314.05
XS Rating Curve= 0 ,0
Exp/Cntr(USF)=0,0
Exp/Cntr=0.3,0.1

Type RM Length L Ch R = 1 ,4000    ,366.9,376.8,378.9
BEGIN DESCRIPTION:
Structure XS 4
END DESCRIPTION:
XS GIS Cut Line= 6
1598618.45453408396376.2400259231598704.21617359396414.108388498
1598784.25997676396449.4528060111599012.95702593396550.436199844
1599093.00148526 396585.779633091599183.32906051396614.408512846
#Sta/Elev= 30
       0  742.32    19.3  739.61    54.3  732.38    71.8  729.71   102.4  727.27
   150.5  724.42   159.2  721.65   163.6  721.01   176.7  721.77   188.9  719.63
   198.6  713.39   210.8  708.78   219.9  705.56   238.1  700.87   251.1  696.38
   255.4  694.07   259.8  690.53   272.9  682.54   281.7  675.45   290.4  667.17
   294.8  664.37   304.8  663.31   313.2664.3206     321  666.96   360.4  667.12
   380.6  669.35   459.5  671.49   538.8  672.33   568.2  671.97   613.5  673.95
#Mann= 6 ,-1,0
       0      .1       0   294.8    .045       0   313.2      .1       0
  366.25     .06       0  471.25     .07       0  481.25     .06       0
Bank Sta=294.8,313.2
XS Rating Curve= 0 ,0
Exp/Cntr(USF)=0,0
Exp/Cntr=0.3,0.1

Type RM Length L Ch R = 1 ,3623    ,54.2,52,53.1
BEGIN DESCRIPTION:
Structure XS 3
END DESCRIPTION:
XS GIS Cut Line= 4
1598502.20706419396688.1907502741598748.72359933396784.342427884
1598836.69215545396884.585666243 1599050.4762046396936.753065797
#Sta/Elev= 30
       0  721.23    62.2  716.06      78  716.35    88.2  714.84   156.2  697.82
   186.7  685.33   208.1  678.51   227.2  670.77   261.2  668.61   272.8  669.58
   301.2  666.13   318.1  660.25   323.4  659.93  341.15660.2495     350  662.72
   366.8  664.54   422.1  664.34   430.3  665.45   433.9  668.37   438.6  676.39
   442.7  682.01   450.9  689.42   467.4  697.44   496.2  714.12   506.7  719.01
   541.5  740.74   553.8  746.41   576.2  754.77   599.1  762.07     618  765.82
#Mann= 8 ,-1,0
       0      .1       0     210     .06       0   274.6     .07       0
   318.1    .045       0  341.15     .07       0   374.6      .1       0
  417.97     .07       0  517.97      .1       0
Bank Sta=318.1,341.15
XS Rating Curve= 0 ,0
Exp/Cntr(USF)=0,0
Exp/Cntr=0.3,0.1

Type RM Length L Ch R = 1 ,3571    ,236,231.2,223.4
BEGIN DESCRIPTION:
Structure XS 2
END DESCRIPTION:
XS GIS Cut Line= 5
  1598484.817931396739.3352596411598705.76221147396817.074913879
 1598743.6091484396853.898960623 1598799.8681087  396920.3868228
1599038.20152235396974.600002728
#Sta/Elev= 30
       0  726.47    12.9  724.98    37.4  723.99    75.6  717.75   126.5  703.35
   138.4  698.71   147.7  694.03   173.1  684.31   208.5  677.15   228.2  671.02
   269.4  666.72     294  665.45   303.4  660.81   306.4  659.97     312  660.07
   321.9  658.97  330.58 660.075   340.3  662.15   382.6  664.73   403.1  663.48
   414.6  665.34   419.5  668.98   435.9  686.13   444.1     692   464.5  702.72
   494.8  716.15   544.9  743.88   554.9  748.27   583.6  757.79   618.5  763.81
#Mann= 7 ,-1,0
       0      .1       0     180     .06       0  307.03      .1       0
     312    .045       0  330.58      .1       0  434.12     .07       0
  534.12      .1       0
Bank Sta=312,330.58
XS Rating Curve= 0 ,0
Exp/Cntr(USF)=0,0
Exp/Cntr=0.3,0.1

Type RM Length L Ch R = 1 ,3340    ,339.1,338.9,338.8
BEGIN DESCRIPTION:
Structure XS 1
END DESCRIPTION:
XS GIS Cut Line= 2
1598437.18973776397065.8601996531599030.60498336397138.141403072
#Sta/Elev= 30
       0  723.22      23  718.43    55.3   713.5    99.7  711.42   131.9  707.69
     152  703.51   184.3  695.18   196.4  690.77   200.4  688.56   224.6  669.95
  256.23657.5839   260.8  657.25269.6616657.5776     277  657.86     289  660.45
   357.5  661.34   377.7  663.54   389.8  666.65   405.9  666.89     414  670.28
   426.1  672.84   434.1  676.78   446.9  681.12   474.4  692.36   498.6  700.84
   526.8  714.33   555.5   724.7   571.1   734.4   578.4  737.93   597.8   741.2
#Mann= 6 ,-1,0
       0     .05       0      20      .1       0  256.23    .045       0
269.6616      .1       0     320     .06       0     420      .1       0
Bank Sta=256.23,269.6616
XS Rating Curve= 0 ,0
Exp/Cntr(USF)=0,0
Exp/Cntr=0.3,0.1