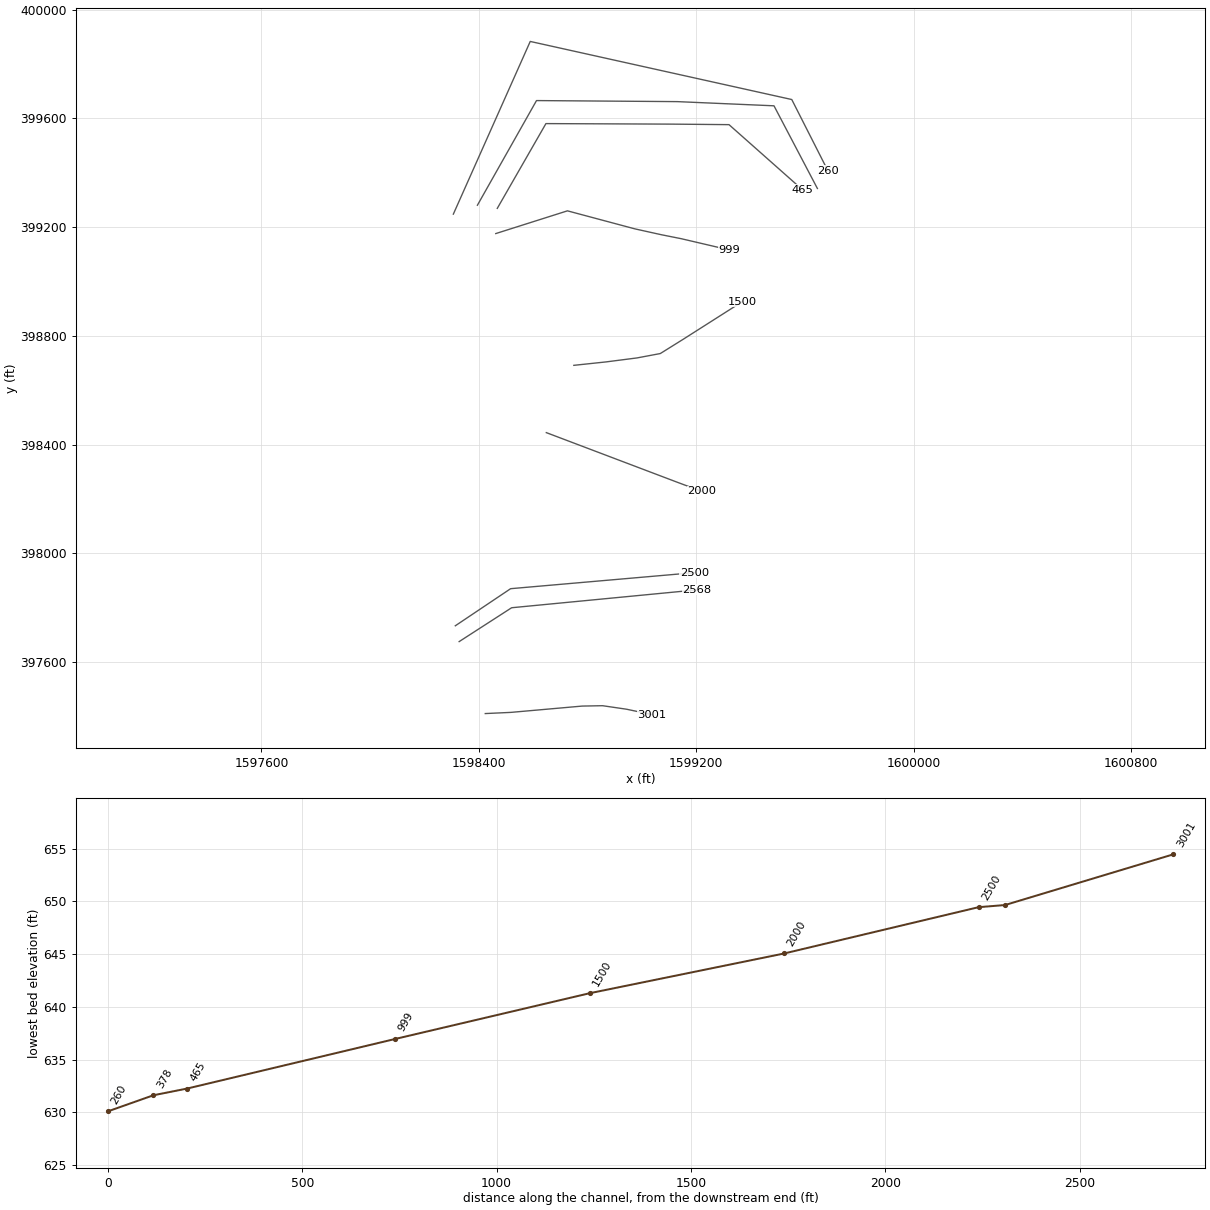
HEC-RAS study HUPPRN.prj: HUPPRN

--- HUPPRN.g01 (geometry) --- (continued)

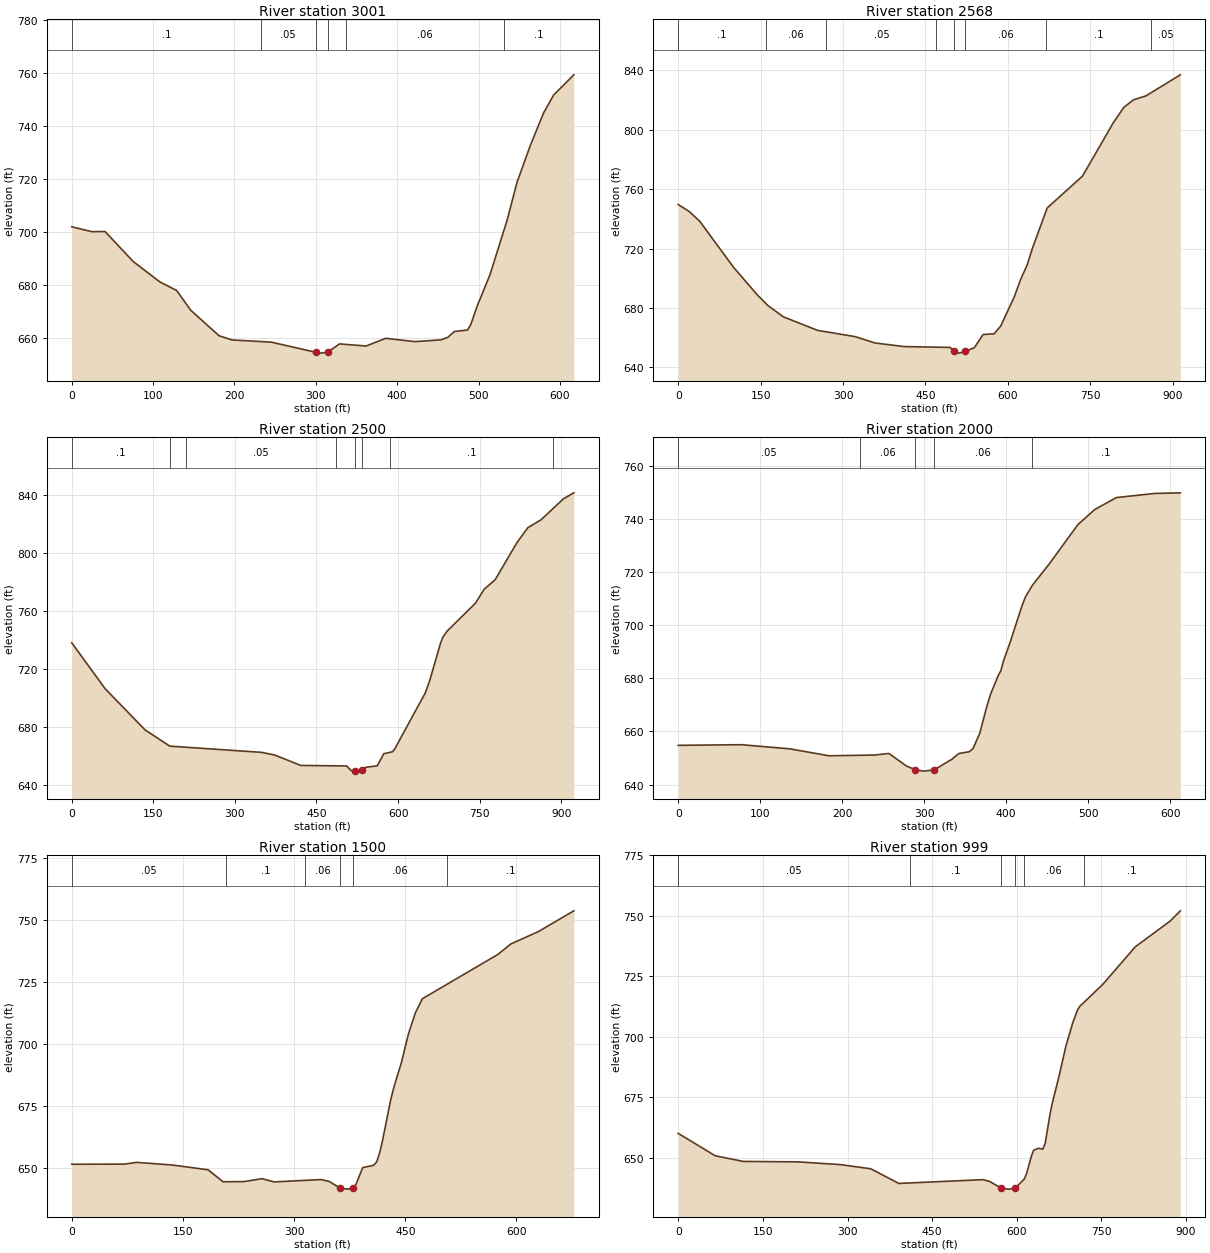
Type RM Length L Ch R = 1 ,3001    ,431.2,433.3,433.5
BEGIN DESCRIPTION:
Structure 2 XS 4
END DESCRIPTION:
XS GIS Cut Line= 6
1598423.41030475397410.5115794241598517.69522117397414.854090422
  1598779.863332 397438.038099171598854.90550476 397439.43803075
1598942.63826892397426.609972417  1599036.354945397406.920051172
#Sta/Elev= 30
       0  702.11    24.7  700.26    40.9  700.33    75.3  689.07   108.4  681.29
   128.9   678.1   146.2  670.64   181.1     661   197.2  659.43   245.5  658.59
  299.59654.8021   305.7  654.46   314.6654.8217     329  657.94   361.8  657.14
   385.8  660.05   421.9  658.79   453.9  659.47   462.2  660.43   470.3  662.61
   486.4  663.17   490.5  665.26   498.5  672.39   513.9  683.92   535.1  704.61
   547.3  718.91   563.7  732.84     580  745.09   592.3  751.81   617.1  759.41
#Mann= 6 ,-1,0
       0      .1       0  232.27     .05       0  299.59    .045       0
   314.6     .05       0  337.57     .06       0  531.31      .1       0
Bank Sta=299.59,314.6
XS Rating Curve= 0 ,0
Exp/Cntr(USF)=0,0
Exp/Cntr=0.3,0.1

Type RM Length L Ch R = 1 ,2568    ,68,67.6,67.5
BEGIN DESCRIPTION:
Structure 2 XS 3
END DESCRIPTION:
XS GIS Cut Line= 3
1598327.33583525397675.2439325381598520.46875441397799.773652615
1599201.28093663397865.394103913
#Sta/Elev= 30
       0  749.64      20  744.91      39  738.42   100.9  707.29   143.7  688.91
   163.5  681.58   191.3  674.08   253.6  664.96   321.9  660.75     358   656.5
   410.3  654.07   494.7  653.49   502.7  650.81   510.7  649.65   522.8  650.84
   538.9  653.29   554.9  662.17     575  662.68   587.1  667.95   611.4  687.35
   623.3  699.31   635.3  709.17   644.3  719.83   671.5  747.28   735.8  768.74
     792  804.72   811.1  814.97   828.2  819.96   851.2  822.69   913.8  836.85
#Mann= 8 ,-1,0
       0      .1       0     160     .06       0   269.8     .05       0
   469.8     .06       0   502.7    .045       0   522.8     .06       0
   669.8      .1       0   859.8     .05       0
Bank Sta=502.7,522.8
XS Rating Curve= 0 ,0
Exp/Cntr(USF)=0,0
Exp/Cntr=0.3,0.1

Type RM Length L Ch R = 1 ,2500    ,500.2,500.1,495.1
BEGIN DESCRIPTION:
Structure 2 XS 2
END DESCRIPTION:
XS GIS Cut Line= 3
1598313.16778326 397733.407514371598516.74031968397869.868225592
1599192.33269327397928.777494371
#Sta/Elev= 30
       0  738.04    61.3  706.36   134.9  677.89   180.2  666.71   348.8  662.41
   372.9   660.6   421.1  653.38   505.4  653.03   513.5  649.82   521.5  649.85
   529.5  649.45  534.44649.9103   541.6  652.13   561.6  653.08   573.7  661.46
   589.8  662.83   593.8  664.73     650   703.4     658  711.71   678.1   737.8
   682.1  741.68   690.1  746.07   742.3  765.38   758.4  775.04   778.5  781.56
   818.6  807.21   838.7  817.51   862.8  822.92   904.3  837.49   923.2  841.55
#Mann= 8 ,-1,0
       0      .1       0     180     .06       0     210     .05       0
  485.08     .06       0   521.5    .045       0  534.44     .06       0
  585.08      .1       0  885.08     .05       0
Bank Sta=521.5,534.44
XS Rating Curve= 0 ,0
Exp/Cntr(USF)=0,0
Exp/Cntr=0.3,0.1

Type RM Length L Ch R = 1 ,2000    ,492.4,500.5,507.5
BEGIN DESCRIPTION:
Structure 2 XS 1
END DESCRIPTION:
XS GIS Cut Line= 6
1598648.06799193398443.9048538361598887.70268326398353.134366095
1598981.21890043398317.7125209271599051.35589926398291.145316839
1599133.18250726398260.1509562581599221.07636034398227.529958501
#Sta/Elev= 30
       0  654.76      77     655     136  653.45     184  650.83   239.6  651.11
     257  651.71   278.7  646.92  289.29645.5896   299.5  645.06   312.3  645.56
   333.7  649.49   342.2  651.67   355.1  652.37   359.6  653.53   367.9  659.37
   376.5  669.47   381.1  674.04   390.4  681.05   393.6  682.85   396.6  686.34
   404.7  693.33   419.2  707.12   423.5  710.56   432.1  714.99   452.5  722.96
   487.7  737.84   508.3  743.51   534.7  747.98   581.6  749.52   612.5  749.75
#Mann= 5 ,-1,0
       0     .05       0  221.25     .06       0  289.29    .045       0
   312.3     .06       0  431.25      .1       0
Bank Sta=289.29,312.3
XS Rating Curve= 0 ,0
Exp/Cntr(USF)=0,0
Exp/Cntr=0.3,0.1

Type RM Length L Ch R = 1 ,1500    ,507.7,500.5,491.3
XS GIS Cut Line= 6
1598749.34567651398691.4309335951598866.84314492398703.894491345
1598981.81240317398718.6739893411599067.48710059 398734.78747417
1599152.39178643398787.6863185021599368.58164276398925.258221835
#Sta/Elev= 30
       0  651.34    71.2  651.38    87.3  652.09   135.6  651.03     184  649.09
   204.1  644.27   232.4  644.32   256.8  645.51     273   644.2   336.1  645.15
   347.3   644.4   362.4  641.65   372.3  641.29  379.25641.6483   383.3  643.02
   392.6  649.98   407.2   650.9   411.5  652.29   415.9  656.42   418.8  660.11
   430.4  677.41   435.2  683.02   444.9  692.46   454.1  703.73   463.6  712.43
   473.1  718.15   575.3  736.09   592.6  740.28   629.6  745.26   677.5  753.64
#Mann= 6 ,-1,0
       0     .05       0  208.16      .1       0  314.07     .06       0
   362.4    .045       0  379.25     .06       0  506.28      .1       0
Bank Sta=362.4,379.25
XS Rating Curve= 0 ,0
Exp/Cntr(USF)=0,0
Exp/Cntr=0.3,0.1

Type RM Length L Ch R = 1 ,999     ,510.7,533.8,535.4
BEGIN DESCRIPTION:
Structure 1 XS 4
END DESCRIPTION:
XS GIS Cut Line= 6
1598462.12075094399176.1141104991598725.76768912399259.707394672
1598974.03485967399193.3725150081599071.69673784399171.780038506
1599145.24022593399157.0714064991599321.69984676399115.829034925
#Sta/Elev= 30
       0  660.02    65.6  650.74   115.4  648.41   212.2  648.23   287.3   647.1
   341.3  645.36     391   639.3   539.8  640.87   552.1  640.12 572.541637.2869
   586.3  636.95597.1409637.3188   613.5  641.19   617.6  643.56   625.8  650.57
   629.9  653.06   638.1  653.86   646.2  653.49   650.3  655.86   658.5  667.42
   662.6  672.18   674.8  683.61     687  696.09   699.3  705.84   707.4  710.95
   711.5  712.54   752.6  721.72   810.1  737.23   871.7  747.84   889.8   752.1
#Mann= 6 ,-1,0
       0     .05       0  410.78      .1       0 572.541    .045       0
597.1409      .1       0  613.56     .06       0  718.58      .1       0
Bank Sta=572.541,597.1409
XS Rating Curve= 0 ,0
Exp/Cntr(USF)=0,0
Exp/Cntr=0.3,0.1

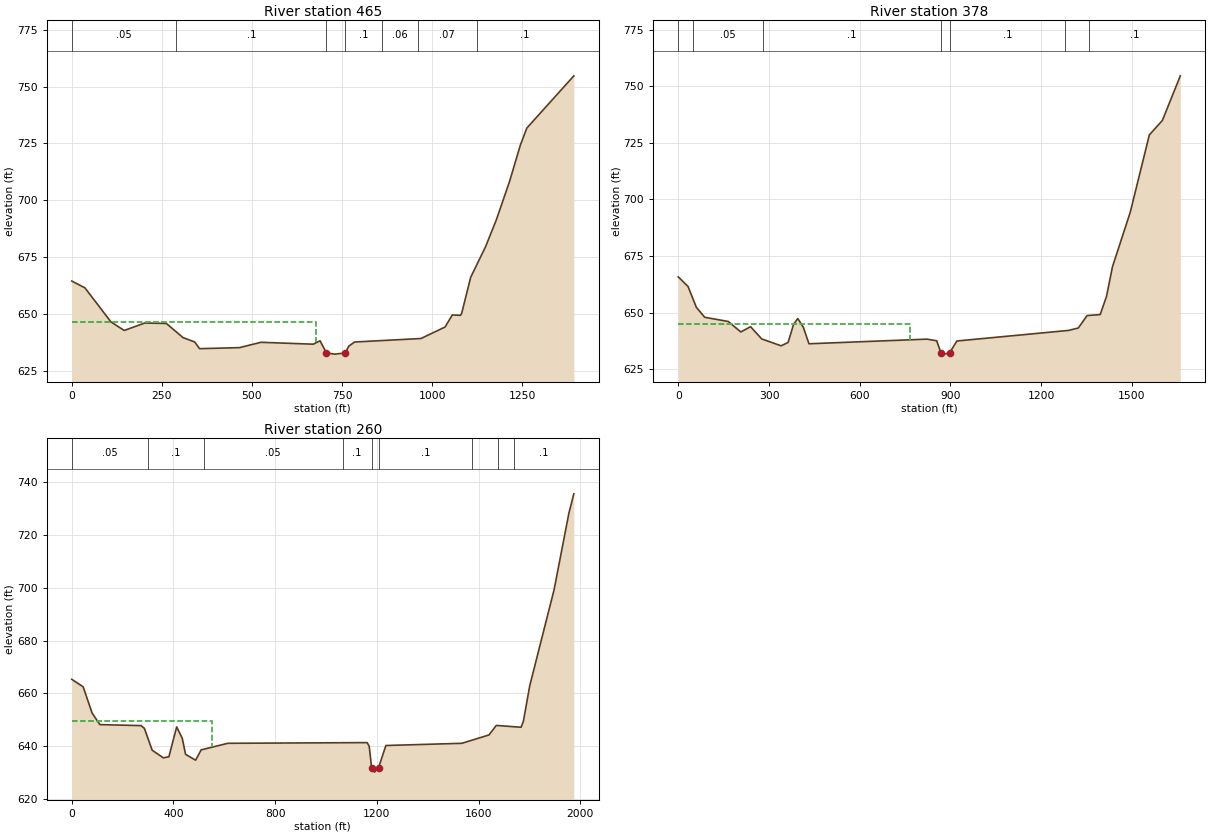
Type RM Length L Ch R = 1 ,465     ,95.9,87.3,86.7
BEGIN DESCRIPTION:
Structure 1 XS 3
END DESCRIPTION:
XS GIS Cut Line= 5
1598467.63164938399268.8071865151598646.63324584399580.616419052
1599106.64810125399578.6916707031599320.29516799399576.766922354
1599589.75993685399338.098127079
#Sta/Elev= 30
       0  664.43    36.6  661.42   108.6  646.46   145.6  642.68   202.6  645.95
   262.6  645.75   308.7  639.54     341  637.62   354.8  634.66   465.4  635.12
     525  637.47   670.2  636.63     689  638.13   706.6 632.814     729  632.26
  758.98632.7665     769  635.82     785   637.6     969  639.13  1036.1  644.21
  1055.9  649.51  1078.6  649.33  1081.8  650.11  1106.9  666.06  1148.2  679.53
  1177.8  691.22  1214.6  708.14  1244.7   724.2  1262.7  731.73  1393.2  754.73
#Mann= 7 ,-1,0
       0     .05       0     290      .1       0   706.6    .045       0
  758.98      .1       0  859.56     .06       0  959.56     .07       0
 1123.21      .1       0
#XS Ineff= 2 , 0
          678.41  646.34
Permanent Ineff=
       F       F
Bank Sta=706.6,758.98
XS Rating Curve= 0 ,0
Exp/Cntr(USF)=0,0
Exp/Cntr=0.3,0.1

Type RM Length L Ch R = 1 ,378     ,119.5,117.4,113.8
BEGIN DESCRIPTION:
Structure 1 XS 2
END DESCRIPTION:
XS GIS Cut Line= 5
1598394.49121212399280.3556766091598611.98777556399665.305346407
1599129.74508144399661.455849709  1599485.823526399646.057862917
1599645.57763897399341.947623777
#Sta/Elev= 30
       0  665.77    32.4  661.52    59.9  652.31    87.5  647.91   165.6  646.04
   206.8  641.42   239.1  643.75   275.9  638.35   340.2  635.29   363.2  636.78
   381.5  644.86   395.3  647.35   413.7  643.47   432.1   636.2   822.3  638.24
   854.3  637.53   868.7  632.16   878.3  631.62   896.9  632.15   921.1  637.42
  1290.6   642.1  1322.6  643.17  1351.7  648.66  1394.9  649.09  1415.9  657.15
  1435.5  670.21  1494.3  694.32  1557.5  728.52  1600.6   734.9  1659.8  754.61
#Mann= 7 ,-1,0
       0     .06       0      50     .05       0     280      .1       0
   868.7    .045       0   896.9      .1       0 1279.92     .07       0
 1356.33      .1       0
#XS Ineff= 2 , 0
          767.18  644.95
Permanent Ineff=
       F       F
Bank Sta=868.7,896.9
XS Rating Curve= 0 ,0
Exp/Cntr(USF)=0,0
Exp/Cntr=0.3,0.1

Type RM Length L Ch R = 1 ,260     ,,,
BEGIN DESCRIPTION:
Structure 1 XS 1
END DESCRIPTION:
XS GIS Cut Line= 4
1598305.95278807399247.6349546761598588.89079537399882.801909843
1599551.26496987399669.1548431051599684.07260595399407.389067642
#Sta/Elev= 30
       0   665.3    44.8  662.47    79.8  652.54   110.5  648.12   272.5  647.74
   285.6  646.71   316.3   638.4   360.1  635.51     382  635.92   412.6  647.25
   434.5  642.96   447.6  636.84     487  634.62   508.9  638.54     614  641.03
  1161.6  641.29  1169.8  639.92  1179.4  631.75  1190.3  630.09  1206.7  631.78
  1235.4  640.19  1534.5  641.03    1641   644.2  1669.7  647.81  1767.1  647.12
    1776  649.27  1801.3  662.88  1897.1  699.34  1955.4  728.42  1974.7  735.69
#Mann= 9 ,-1,0
       0     .05       0     300      .1       0     520     .05       0
 1065.34      .1       0  1179.4    .045       0  1206.7      .1       0
 1575.34     .07       0 1675.34     .06       0 1741.14      .1       0
#XS Ineff= 2 , 0
          550.66  649.31
Permanent Ineff=
       F       F
Bank Sta=1179.4,1206.7
XS Rating Curve= 0 ,0
Exp/Cntr(USF)=0,0
Exp/Cntr=0.3,0.1
LCMann Table=0

Chan Stop Cuts=-1
Use User Specified Reach Order=0
Composite Channel Slope=5